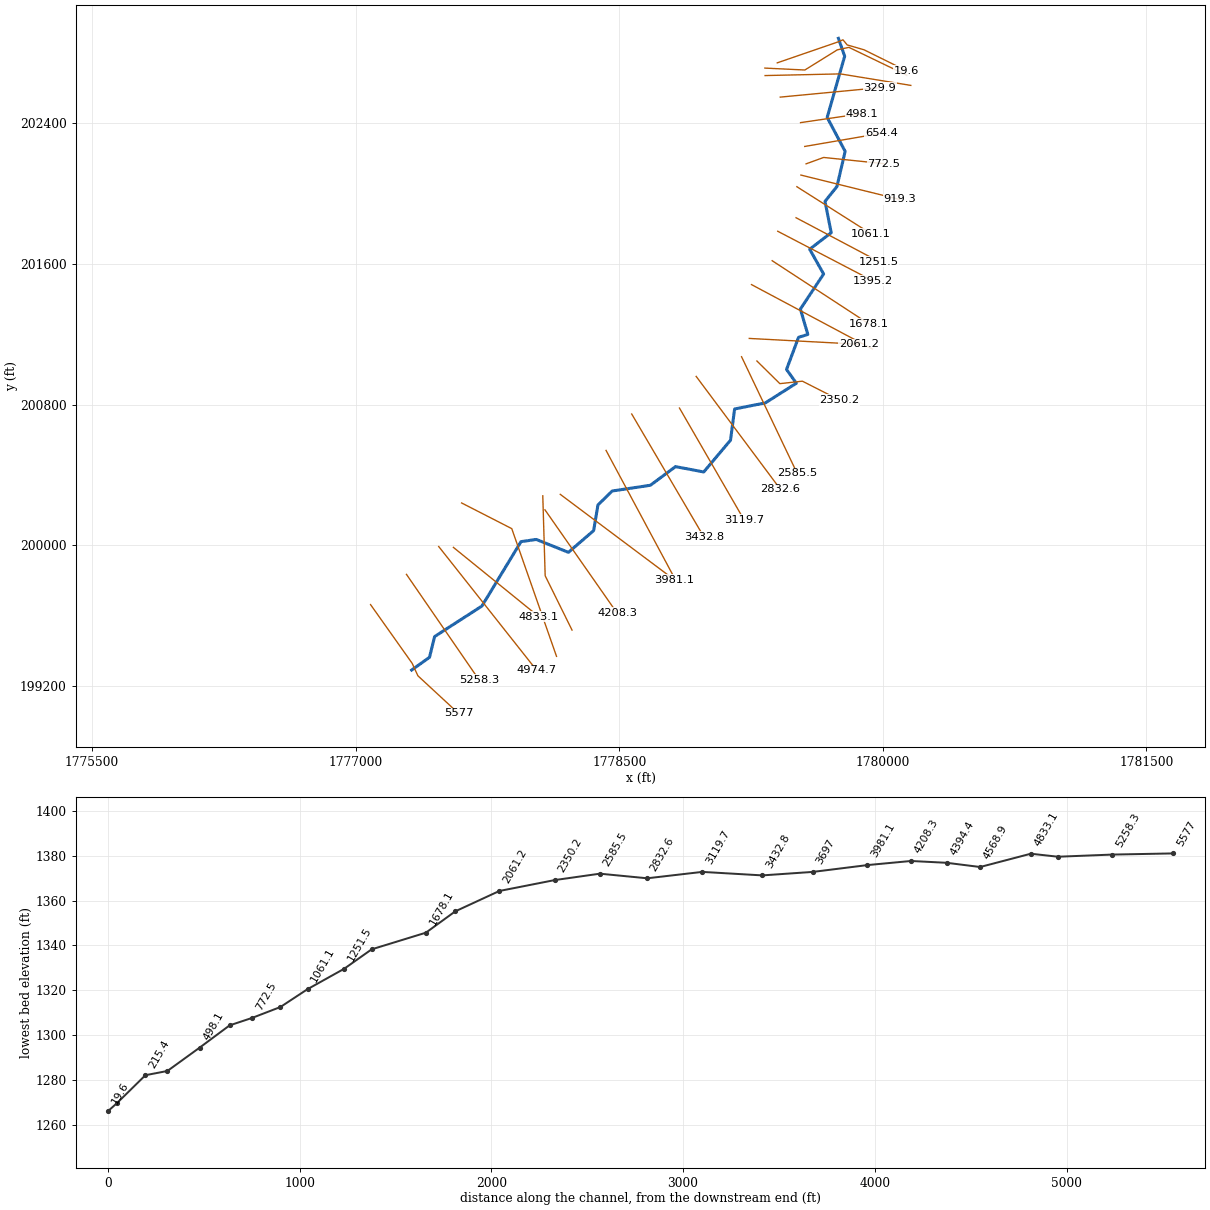
--- TraceFk3.prj (project) ---

Proj Title=TraceFk3
Current Plan=p01
Default Exp/Contr=0,0
English Units
Geom File=g01
Flow File=f01
Plan File=p01
BEGIN DESCRIPTION:
END DESCRIPTION:
DSS Export Rating Curves= 0
DSS Export Rating Curve Sorted= 0
DSS Export Volume Flow Curves= 0
DXF OffsetX= 0
DXF OffsetY= 0
DXF ScaleX= 0
DXF ScaleY= 0

--- TraceFk3.p01 (plan) ---

Plan Title=Floodplain
Program Version=4.00
Geom File=g01
Flow File=f01
K Sum by GR=0
Std Step Tol=0.01
Critical Tol=0.01
Num of Std Step Trials=20
Max Error Tol=0.3
Flow Tol Ratio=0.001
Split Flow NTrial=30
Split Flow Tol=0.02
Split Flow Ratio=0.02
Log Output Level=0
Friction Slope Method=1
Unsteady Friction Slope Method=2
Unsteady Bridges Friction Slope Method=1
Global Log Level=0
CheckData=False
Run HTab=0
Run UNet=0
Run PostProcess=0
UNET Theta=0
UNET Theta Warmup=0
UNET ZTol=0
UNET ZSATol=0
UNET MxIter=0
UNET MaxInSteps=0
UNET DtIC=0
UNET DtMin=0
UNET MaxCRTS=0
UNET WFStab=0
UNET SFStab=0
UNET WFX=0
UNET SFX=0
UNET DSS MLevel=0
UNET DZMax Abort=0
UNET Convert EG Bridges=0
UNET Use Existing IB Tables=0
UNET Froude Limit=0
UNET Froude Power=0
Write IC File=0
Echo Input=False
Echo Output=False
Write Detailed=0

--- TraceFk3.f01 (steady flow) ---

Flow Title=NFF Regression Equation
Program Version=4.00
Number of Profiles=1
Profile Names=P100yr
River Rch & RM=TraceFk3,Main      ,5577
736.2047
River Rch & RM=TraceFk3,Main      ,5577
490.9716
River Rch & RM=TraceFk3,Main      ,3697
782.4635
River Rch & RM=TraceFk3,Main      ,3697
526.4671
River Rch & RM=TraceFk3,Main      ,215.4
847.5569
River Rch & RM=TraceFk3,Main      ,215.4
577.1443
Boundary for River Rch & Prof#=TraceFk3,Main      ,1
Up Type=0
Dn Type=3
Dn Slope=0.055932

--- TraceFk3.g01 (geometry) ---

Geom Title=USGS 10m DEM
Program Version=4.00

River Reach=TraceFk3        ,Main
Reach XY= 30
     1777318.237      199289.266     1777419.877      199361.787
     1777448.995      199479.909     1777718.203       199653.52
     1777940.447      200019.913     1778027.364      200032.466
     1778210.151      199959.098     1778353.817      200082.492
     1778378.495      200228.801     1778459.582      200308.126
     1778676.913      200340.824     1778819.758       200446.86
     1778980.481      200416.536     1779132.727      200597.209
     1779156.213      200774.884     1779330.624      200809.354
     1779507.607      200921.512     1779451.528      200999.714
     1779519.888      201182.459     1779572.771      201199.206
     1779530.464      201343.753     1779662.672      201542.945
     1779583.348      201683.967      1779705.86      201778.275
     1779670.605      201956.315     1779738.471      202040.928
     1779785.185      202241.002     1779682.944      202434.025
      1779782.54      202782.172     1779746.836      202884.202

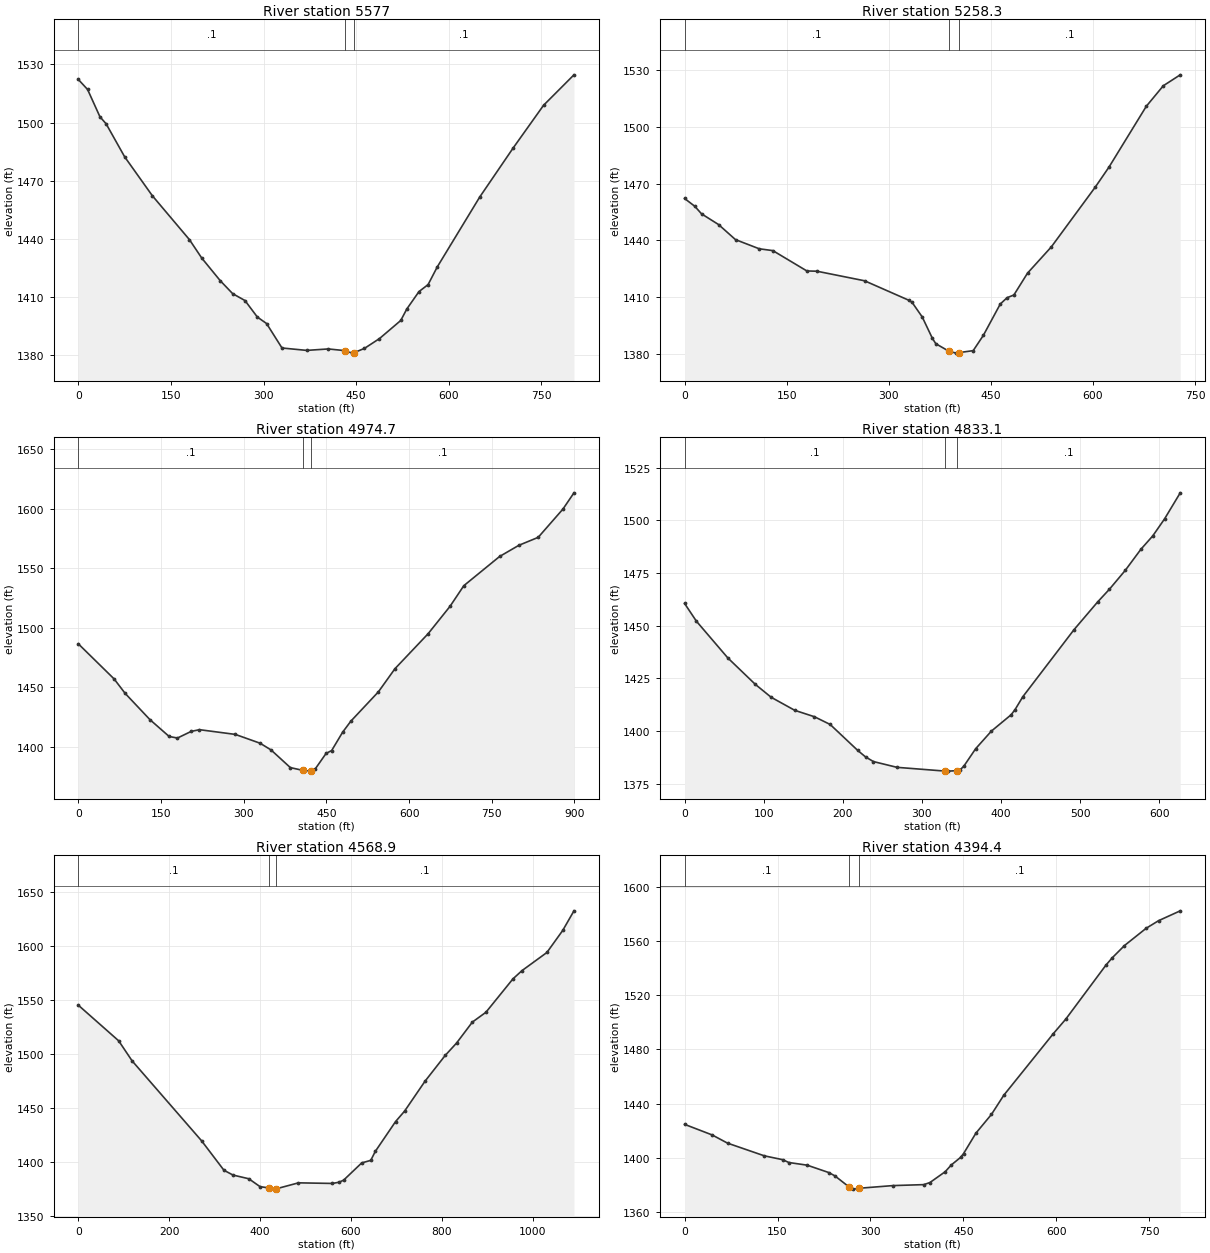
Type RM Length L Ch R = 1 ,5577    ,315.6,318.7,320.2
XS GIS Cut Line= 4
     1777084.328      199661.735     1777321.252      199327.365
     1777353.734       199256.67     1777584.926      199042.674
#Sta/Elev= 30
       0 1522.25      15 1517.08      35    1503      45 1499.38      75 1482.35
   119.9 1462.25   179.9 1439.62   199.9 1430.09   229.9  1418.4   249.9 1411.75
   269.9 1408.18   289.9 1399.67   304.8 1396.34   329.8 1383.71   369.8 1382.47
   404.8 1383.22   431.2 1382.36   443.8 1381.06   446.2 1381.26   463.3  1383.5
   487.6 1388.55   522.1  1397.9   531.9 1403.82   551.6  1412.8   566.4 1416.42
   581.1 1425.46     650  1461.6   704.2 1486.93   753.4 1508.94   802.6 1524.64
#Mann= 3 , 0 , 0
       0      .1       0   431.2    .045       0   446.2      .1       0
Bank Sta=431.2,446.2
XS Rating Curve= 0 ,0
Exp/Cntr=0.3,0.1

Type RM Length L Ch R = 1 ,5258.3  ,281.3,283.6,285.9
XS GIS Cut Line= 2
     1777288.771      199833.696     1777701.478      199233.742
#Sta/Elev= 30
       0 1462.15      15 1458.02    24.9 1454.04    49.9 1448.39    74.8 1440.43
   109.7  1435.6   129.7 1434.63   179.6 1423.91   194.5 1423.76   264.4 1418.72
   329.2 1408.48   334.2 1407.34   349.1 1399.64   364.1 1388.31   369.1  1385.5
   388.3 1381.55     399 1380.54   403.3 1380.82     424 1381.85   438.9  1389.9
   463.8 1406.46   473.8 1409.79   483.8 1411.22   503.8 1422.74   538.7 1436.56
   603.5 1468.22   623.5  1478.7   678.3 1510.78   703.3 1521.63   728.2  1527.4
#Mann= 3 , 0 , 0
       0      .1       0   388.3    .045       0   403.3      .1       0
Bank Sta=388.3,403.3
XS Rating Curve= 0 ,0
Exp/Cntr=0.3,0.1

Type RM Length L Ch R = 1 ,4974.7  ,136.4,141.6,146.6
XS GIS Cut Line= 2
     1777472.196      199992.282     1778030.115      199287.241
#Sta/Elev= 30
       0 1486.59    64.9 1457.09    84.9 1444.96   129.9 1422.87   164.8  1408.7
   179.8  1407.4   204.8 1412.98   219.8 1414.42   284.7 1410.46   329.7 1403.05
   349.6 1397.39   384.6 1382.55   406.8 1380.27   419.6 1379.58   421.8 1379.72
   429.6 1381.33   449.5 1394.51   459.5 1396.85   479.5 1412.34   494.5 1421.65
   544.4 1446.27   574.4  1465.7   634.4 1495.02   674.3 1518.13   699.3 1535.47
   764.2 1560.02   799.2 1569.43   834.2  1576.1   879.1 1599.88   899.1 1613.53
#Mann= 3 , 0 , 0
       0      .1       0   406.8    .045       0   421.8      .1       0
Bank Sta=406.8,421.8
XS Rating Curve= 0 ,0
Exp/Cntr=0.3,0.1

Type RM Length L Ch R = 1 ,4833.1  ,281.9,264.3,214.4
XS GIS Cut Line= 2
     1777555.802      199987.394     1778042.451      199592.839
#Sta/Elev= 30
       0 1460.54    14.9 1452.13    54.7 1434.65    89.5 1422.09   109.4    1416
   139.2  1409.8   164.1 1406.75     184 1403.08   218.8 1390.77   228.7 1387.67
   238.7 1385.46   268.5 1382.72   329.4 1380.93   333.1 1380.92   344.4 1381.14
     348 1381.42     353  1383.3   367.9 1391.56   387.8 1399.93   412.7 1407.67
   417.7 1410.14   427.6 1416.29   492.2 1448.08   522.1 1461.27     537  1467.3
   556.9 1476.21   576.8 1486.29   591.7  1492.6   606.6 1500.66   626.5 1513.08
#Mann= 3 , 0 , 0
       0      .1       0   329.4    .045       0   344.4      .1       0
Bank Sta=329.4,344.4
XS Rating Curve= 0 ,0
Exp/Cntr=0.3,0.1

Type RM Length L Ch R = 1 ,4568.9  ,173.9,174.5,206.8
XS GIS Cut Line= 3
     1777602.547       200240.14     1777887.875      200094.079
     1778142.633      199367.171
#Sta/Elev= 30
       0  1545.4    88.8  1512.4   118.4  1493.8   271.2  1419.8   320.5 1392.46
   340.4 1388.03   375.2  1384.6     400 1377.26   420.4 1376.09   429.9 1374.99
   435.4 1375.27   484.5 1380.81   559.1 1380.26     574  1381.4   583.9 1383.33
   623.7 1399.29   643.6 1401.63   653.5  1409.9   698.2 1437.58   718.1  1447.3
   762.8 1474.86   807.5 1498.89   832.4 1510.32   867.2 1529.74     897 1538.83
   956.6 1569.82   976.5 1577.46  1031.2 1594.22    1066 1614.62  1090.8 1632.82
#Mann= 3 , 0 , 0
       0      .1       0   420.4    .045       0   435.4      .1       0
Bank Sta=420.4,435.4
XS Rating Curve= 0 ,0
Exp/Cntr=0.3,0.1

Type RM Length L Ch R = 1 ,4394.4  ,173.8,186,198.1
XS GIS Cut Line= 3
     1778064.507      200280.901     1778078.094      199825.735
     1778230.949      199516.629
#Sta/Elev= 30
       0 1424.71    44.6 1416.87    69.3 1410.84   128.7 1401.46   158.4 1398.61
   168.3 1396.53     198 1394.55   232.6 1389.14   242.5 1386.71   265.9 1378.35
   272.2 1376.87   280.9 1377.48   336.6 1379.49   386.1 1380.19     396 1381.71
   420.7 1389.72   430.6 1394.73   445.5 1400.29   450.4 1403.14   470.4 1418.26
   495.4 1432.05   515.3  1446.2   595.3  1491.7   615.3 1502.36   680.3 1542.34
   690.3 1547.65   710.2 1556.77   745.2 1569.52   765.2 1575.12   800.2  1582.4
#Mann= 3 , 0 , 0
       0      .1       0   265.9    .045       0   280.9      .1       0
Bank Sta=265.9,280.9
XS Rating Curve= 0 ,0
Exp/Cntr=0.3,0.1

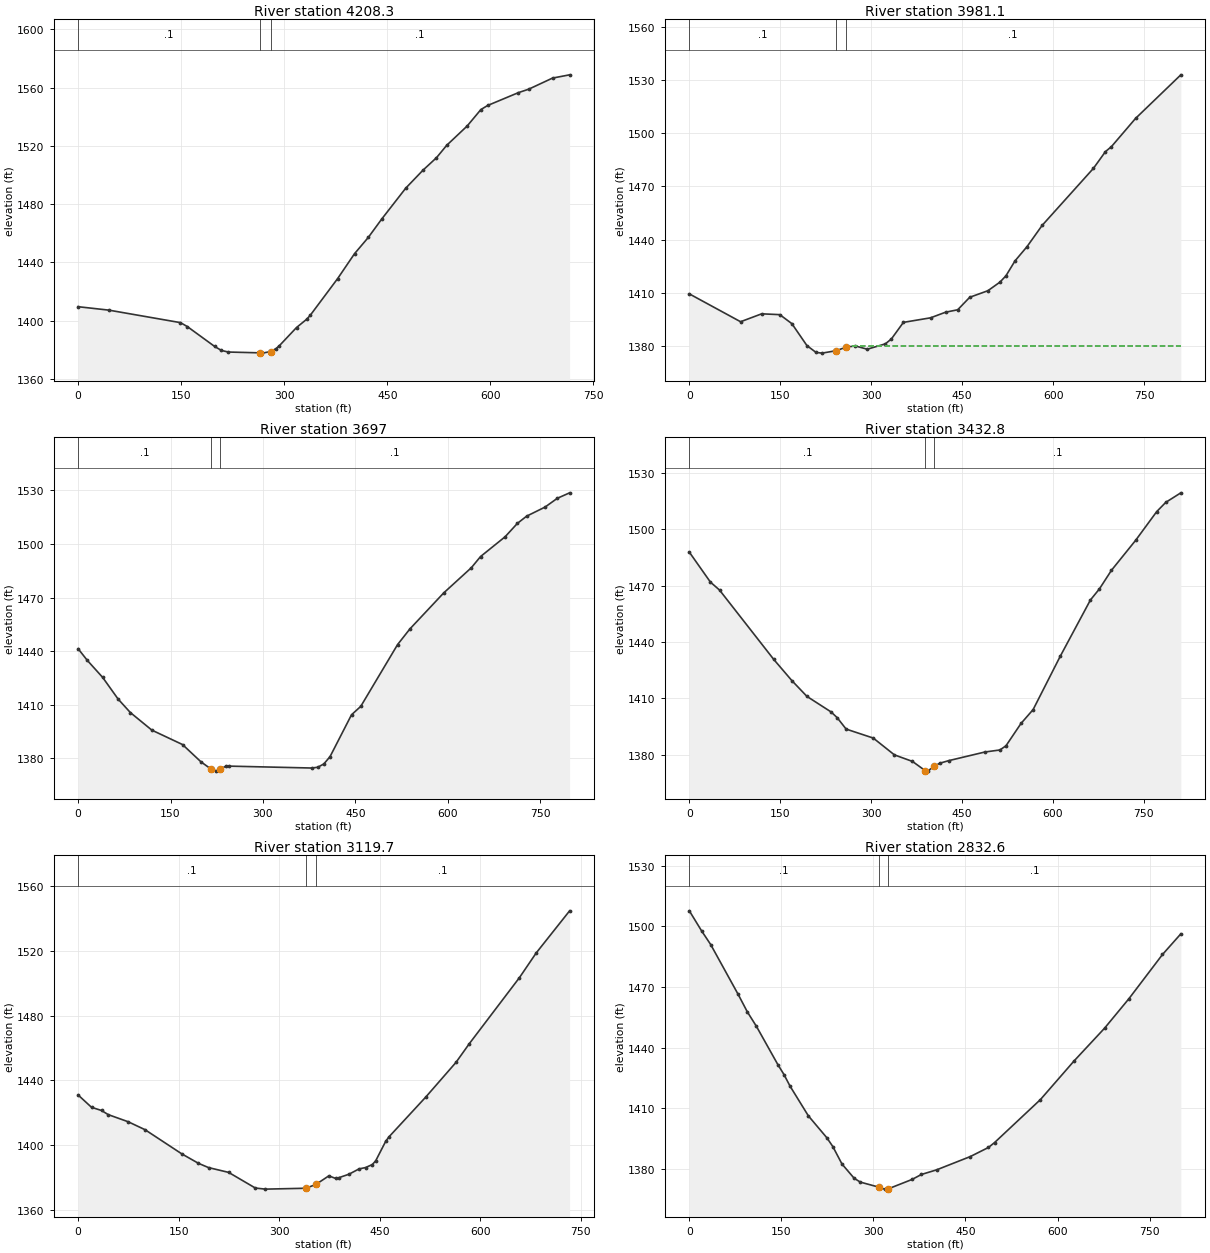
Type RM Length L Ch R = 1 ,4208.3  ,220.3,227.3,233.7
XS GIS Cut Line= 2
     1778076.911       200201.03     1778486.525      199614.547
#Sta/Elev= 30
       0 1409.55    44.7  1407.2     149 1398.61     159  1395.9   198.7 1382.27
   208.6 1379.52   218.6 1378.43   265.2 1377.87   268.3 1377.68   280.2 1378.77
   288.1  1380.8   293.1 1382.86   317.9 1395.26   332.8 1400.98   337.8 1403.61
   377.6 1428.76   402.4 1445.99   422.3 1457.07   442.1 1469.85   476.9 1490.95
   501.8  1503.2   521.6 1511.83   536.5 1520.35   566.3 1533.62   586.2 1544.87
   596.1  1547.7   640.8  1556.5   655.8 1558.87   690.5  1566.5   715.4 1568.74
#Mann= 3 , 0 , 0
       0      .1       0   265.2    .045       0   280.2      .1       0
Bank Sta=265.2,280.2
XS Rating Curve= 0 ,0
Exp/Cntr=0.3,0.1

Type RM Length L Ch R = 1 ,3981.1  ,293.4,284.1,275
XS GIS Cut Line= 2
     1778163.822      200289.236      1778812.67      199803.551
#Sta/Elev= 30
       0 1409.31    84.5 1393.58   119.3 1398.05   149.2 1397.58   169.1 1392.49
   193.9 1380.11   208.8 1376.28   218.8 1375.85   242.6 1377.25   257.6 1379.14
   273.5 1379.93   293.4 1378.06   323.2 1381.08   333.2 1383.86     353 1393.22
   397.8 1395.79   422.6 1398.97   442.5 1400.33   462.4  1407.4   492.3 1411.09
   512.2 1415.95   522.1 1419.52     537 1427.92   556.9 1436.01   581.8 1447.99
   666.3 1480.18   686.2 1489.66   696.1 1492.49   735.9 1508.43   810.5 1533.02
#Mann= 3 , 0 , 0
       0      .1       0   242.6    .045       0   257.6      .1       0
#XS Ineff= 2 , 0
                          268.73         1380.01
Permanent Ineff=
       F       F
Bank Sta=242.6,257.6
XS Rating Curve= 0 ,0
Exp/Cntr=0.3,0.1

Type RM Length L Ch R = 1 ,3697    ,263.4,264.2,264.8
XS GIS Cut Line= 2
     1778424.564      200539.055     1778801.605      199835.925
#Sta/Elev= 30
       0 1441.37      15 1434.81    39.9 1425.28    64.8 1413.23    84.8 1405.61
   119.7 1395.77   169.5 1387.69   199.5 1377.99   215.4 1374.06   224.4 1372.81
   230.4 1373.82   239.4 1375.52   244.3 1375.62     379 1374.55     389 1374.98
   398.9 1376.86   408.9 1380.92   443.8 1404.38   458.8 1409.09   518.6 1443.72
   538.5 1452.44   593.4 1472.62   638.3 1486.75   653.2 1492.99   693.1 1504.08
   713.1  1511.6     728 1515.61     758 1520.72   777.9 1525.64   797.8 1528.69
#Mann= 3 , 0 , 0
       0      .1       0   215.4    .045       0   230.4      .1       0
Bank Sta=215.4,230.4
XS Rating Curve= 0 ,0
Exp/Cntr=0.3,0.1

Type RM Length L Ch R = 1 ,3432.8  ,320.9,313.1,310.2
XS GIS Cut Line= 2
     1778570.625      200746.258     1778981.634      200046.524
#Sta/Elev= 30
       0 1487.89    34.8 1471.94    49.8 1467.72   139.4 1430.74   169.3 1419.46
   194.2 1411.05     234 1402.79     244 1399.76   258.9 1393.64   303.7 1388.86
   338.6  1379.9   368.4 1376.42   389.6 1371.47   393.3 1371.25   404.6 1373.83
   413.2 1375.43   428.2 1376.83   487.9 1381.43   512.8 1382.52   522.8 1384.75
   547.6 1396.64   567.6 1404.03   612.4 1432.44   662.2  1462.4   677.1 1468.33
     697 1478.25   736.8 1494.16   771.7  1509.5   786.6 1514.41   811.5 1519.49
#Mann= 3 , 0 , 0
       0      .1       0   389.6    .045       0   404.6      .1       0
Bank Sta=389.6,404.6
XS Rating Curve= 0 ,0
Exp/Cntr=0.3,0.1

Type RM Length L Ch R = 1 ,3119.7  ,282.8,287,288.1
XS GIS Cut Line= 2
     1778842.367      200780.226     1779209.217      200145.031
#Sta/Elev= 30
       0 1431.01      20 1423.39    34.9 1421.42    44.9 1418.87    74.8 1414.44
    99.8 1409.56   154.7 1394.61   179.6 1388.76   194.6 1386.13   224.6 1383.16
   264.5 1373.48   279.4 1372.81   339.9 1373.35   354.9 1375.72   374.2 1381.02
   384.2 1379.43   389.2 1379.89   404.2 1382.03   419.2  1385.3   429.1 1386.16
   439.1 1388.02   444.1 1390.32   459.1 1402.43   464.1 1405.21     519 1429.81
   563.9 1451.15   583.8 1462.72   658.7 1503.59   683.6 1518.79   733.5 1544.84
#Mann= 3 , 0 , 0
       0      .1       0   339.9    .045       0   354.9      .1       0
Bank Sta=339.9,354.9
XS Rating Curve= 0 ,0
Exp/Cntr=0.3,0.1

Type RM Length L Ch R = 1 ,2832.6  ,250.8,247.1,246
XS GIS Cut Line= 2
     1778937.476      200960.255      1779416.42      200318.266
#Sta/Elev= 30
       0 1507.67    19.9 1497.79    34.8 1490.98    79.6 1466.31    94.5 1457.68
   109.4 1450.48   144.3 1431.56   154.2 1426.68   164.2 1420.88     194 1406.21
   223.9 1395.45   233.8 1391.05   248.8 1382.37   268.6 1375.34   278.6 1373.44
   308.3 1370.98   318.4 1369.96   323.3    1370   363.2 1374.78   378.1  1377.2
     403  1379.5   457.7 1386.05   487.5 1390.58   497.5 1393.02   572.1 1414.25
   626.8 1433.32   676.6 1449.56   716.4 1464.19   771.1 1486.06     801 1496.28
#Mann= 3 , 0 , 0
       0      .1       0   308.3    .045       0   323.3      .1       0
Bank Sta=308.3,323.3
XS Rating Curve= 0 ,0
Exp/Cntr=0.3,0.1

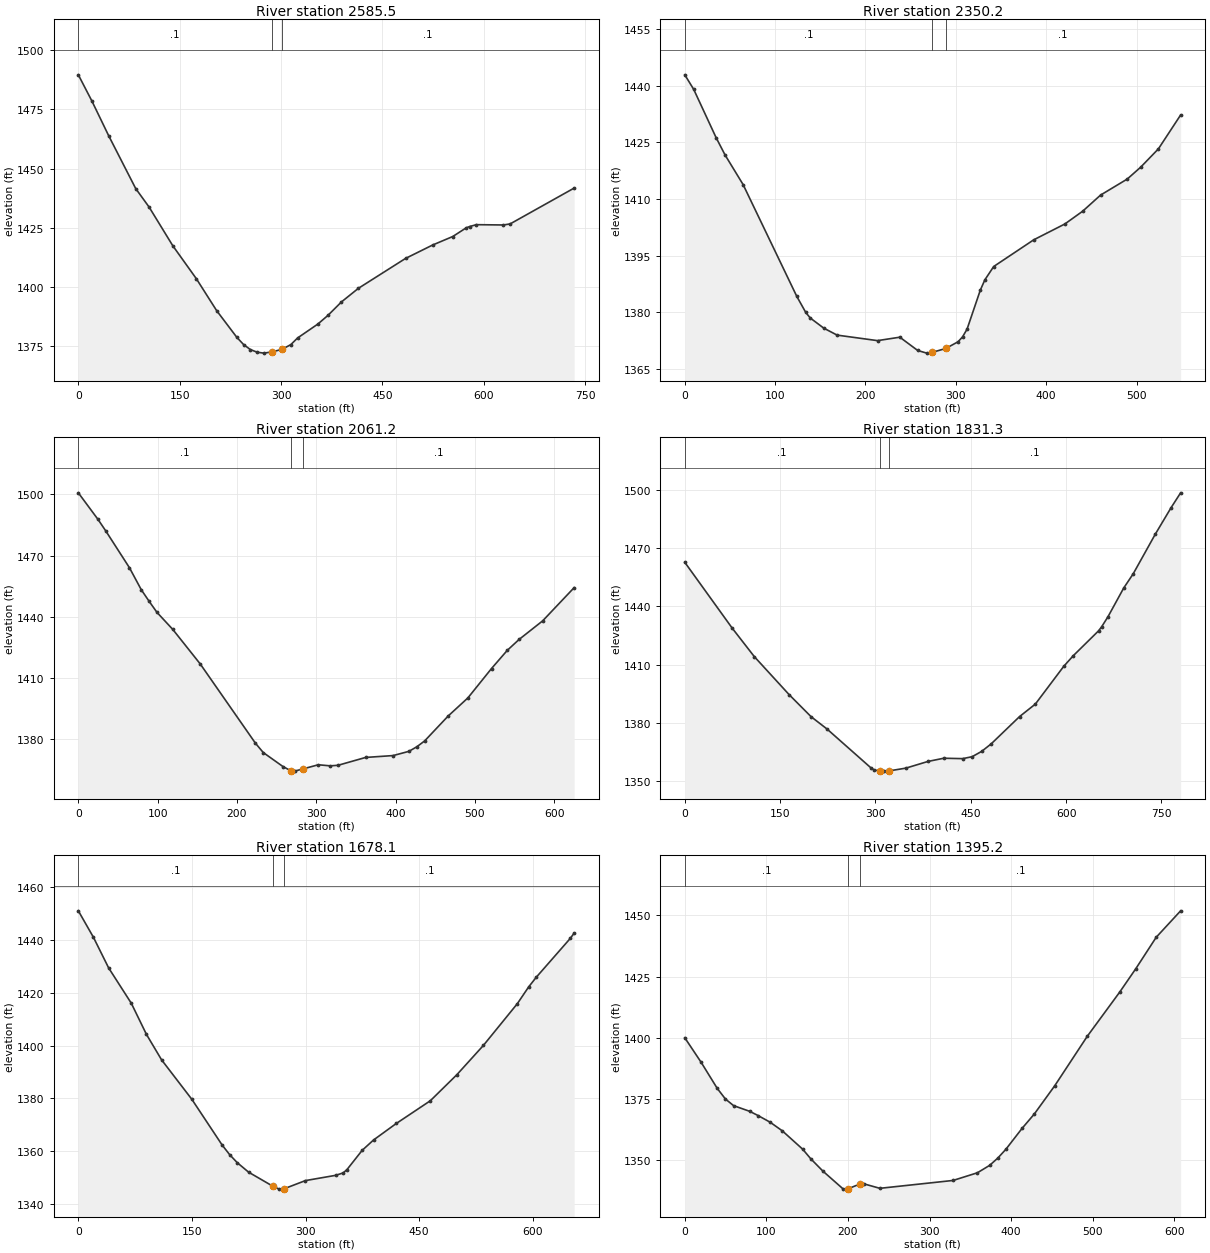
Type RM Length L Ch R = 1 ,2585.5  ,199.2,235.3,264.3
XS GIS Cut Line= 2
      1779195.63      201072.348      1779511.53      200409.978
#Sta/Elev= 30
       0 1489.65      20 1478.62    44.9 1463.91    84.9 1441.58   104.8 1433.72
   139.8  1417.4   174.7 1403.45   204.7 1389.98   234.6 1378.67   244.6 1375.63
   254.6 1373.52   264.6  1372.4   274.6 1372.01   286.1  1372.5   301.1 1373.58
   314.5 1375.61   324.5 1378.42   354.4 1384.28   369.4 1387.96   389.4 1393.65
   414.4 1399.39   484.2 1412.03   524.2 1417.69   554.1  1421.3   574.1 1424.98
   579.1 1425.52   589.1 1426.31     629 1426.18     639 1426.62   733.8 1441.78
#Mann= 3 , 0 , 0
       0      .1       0   286.1    .045       0   301.1      .1       0
Bank Sta=286.1,301.1
XS Rating Curve= 0 ,0
Exp/Cntr=0.3,0.1

Type RM Length L Ch R = 1 ,2350.2  ,299.7,289,284.9
XS GIS Cut Line= 4
      1779283.08      201048.021     1779413.703      200919.092
     1779541.744       200933.17     1779752.655      200826.164
#Sta/Elev= 30
       0 1442.87     9.9    1439    34.7 1426.21    44.6 1421.63    64.5 1413.82
     124 1384.17   133.9 1379.93   138.9 1378.46   153.8 1375.78   168.6 1373.93
   213.3 1372.47     238 1373.38   257.8 1369.86   267.8 1369.16   273.8 1369.36
   288.8 1370.39   302.4 1372.16   307.4 1373.45   312.4  1375.5   327.1 1385.85
   332.1 1388.56   341.9  1392.1   386.2 1399.17   420.7 1403.37   440.4 1406.75
   460.2 1411.02   489.7 1415.26   504.5 1418.39   524.2 1423.26   548.8 1432.23
#Mann= 3 , 0 , 0
       0      .1       0   273.8    .045       0   288.8      .1       0
Bank Sta=273.8,288.8
XS Rating Curve= 0 ,0
Exp/Cntr=0.3,0.1

Type RM Length L Ch R = 1 ,2061.2  ,238.4,229.9,219.7
XS GIS Cut Line= 2
      1779239.41      201176.422     1779863.822      201143.411
#Sta/Elev= 30
       0 1500.75    24.8 1487.72    34.7 1482.01    64.5    1464    79.4 1453.22
    89.3 1447.55    99.2 1442.12   119.1 1433.78   153.8 1416.81   223.3 1378.01
   233.2 1373.41     258 1366.55   268.1 1364.45   272.9 1364.29   283.1 1365.36
   302.7 1367.41   317.6 1366.88   327.5 1367.15   362.3    1371     397 1371.92
   416.9 1373.99   426.8 1376.21   436.7 1379.08   466.5 1391.35   491.3  1400.2
   521.1 1414.61   540.9 1423.49   555.8 1428.84   585.6 1437.98   625.3 1454.27
#Mann= 3 , 0 , 0
       0      .1       0   268.1    .045       0   283.1      .1       0
Bank Sta=268.1,283.1
XS Rating Curve= 0 ,0
Exp/Cntr=0.3,0.1

Type RM Length L Ch R = 1 ,1831.3  ,154.9,153.2,151.5
XS GIS Cut Line= 2
     1779252.243       201482.79     1779940.654       201115.94
#Sta/Elev= 30
       0 1462.56    74.5 1428.75   109.3  1414.1     164 1394.58   198.7 1383.19
   223.6  1376.9   293.1 1356.81   298.1 1355.79   306.4 1355.28     313  1355.2
   321.4 1355.32   347.8 1356.74   382.6 1360.18   407.4 1361.83   437.2 1361.62
   452.1 1362.62     467 1365.34     482  1369.2   526.7 1383.25   551.5 1389.66
   596.2 1409.08   611.1 1414.51   650.9  1427.3   655.8 1429.39   665.8 1434.58
   690.6 1449.37   705.5 1456.66   740.3 1477.06   765.2 1490.72   780.1 1498.29
#Mann= 3 , 0 , 0
       0      .1       0   306.4    .045       0   321.4      .1       0
Bank Sta=306.4,321.4
XS Rating Curve= 0 ,0
Exp/Cntr=0.3,0.1

Type RM Length L Ch R = 1 ,1678.1  ,281.2,282.9,284.6
XS GIS Cut Line= 2
     1779369.998      201618.661     1779918.009      201260.868
#Sta/Elev= 30
       0 1450.95      20  1440.9      40 1429.36    69.9    1416    89.9 1404.22
   109.9 1394.58   149.9 1379.63   189.8 1362.37   199.8  1358.7   209.8 1355.68
   224.8 1352.09     257 1346.74   264.8 1345.72   269.8 1345.68     272 1345.86
   299.8 1348.91   339.7  1350.9   349.7 1351.83   354.7  1353.1   374.7 1360.36
   389.7 1364.27   419.7 1370.51   464.6  1379.1   499.6 1388.94   534.6 1400.01
   579.5 1415.83   594.5 1422.19   604.5 1425.83   649.5 1440.56   654.5 1442.54
#Mann= 3 , 0 , 0
       0      .1       0     257    .045       0     272      .1       0
Bank Sta=257,272
XS Rating Curve= 0 ,0
Exp/Cntr=0.3,0.1

Type RM Length L Ch R = 1 ,1395.2  ,136.8,143.6,144.7
XS GIS Cut Line= 2
     1779401.701      201786.235     1779940.654      201505.436
#Sta/Elev= 30
       0 1400.02    19.9 1390.07    39.8 1379.34    49.8 1375.02    59.8 1372.32
    79.7 1369.98    89.7 1368.29   104.6 1365.56   119.6 1362.01   144.5 1354.54
   154.4 1350.63   169.4 1345.56   194.3 1338.25     200 1338.37     215  1340.4
   219.2 1340.43   239.1 1338.58   328.8 1341.79   358.6 1344.92   373.6 1347.94
   383.6 1350.91   393.5  1354.5   413.4 1363.05   428.4 1368.92   453.3 1380.38
   493.2 1400.58     533 1418.64   552.9 1428.27   577.8 1441.04   607.7 1451.82
#Mann= 3 , 0 , 0
       0      .1       0     200    .045       0     215      .1       0
Bank Sta=200,215
XS Rating Curve= 0 ,0
Exp/Cntr=0.3,0.1

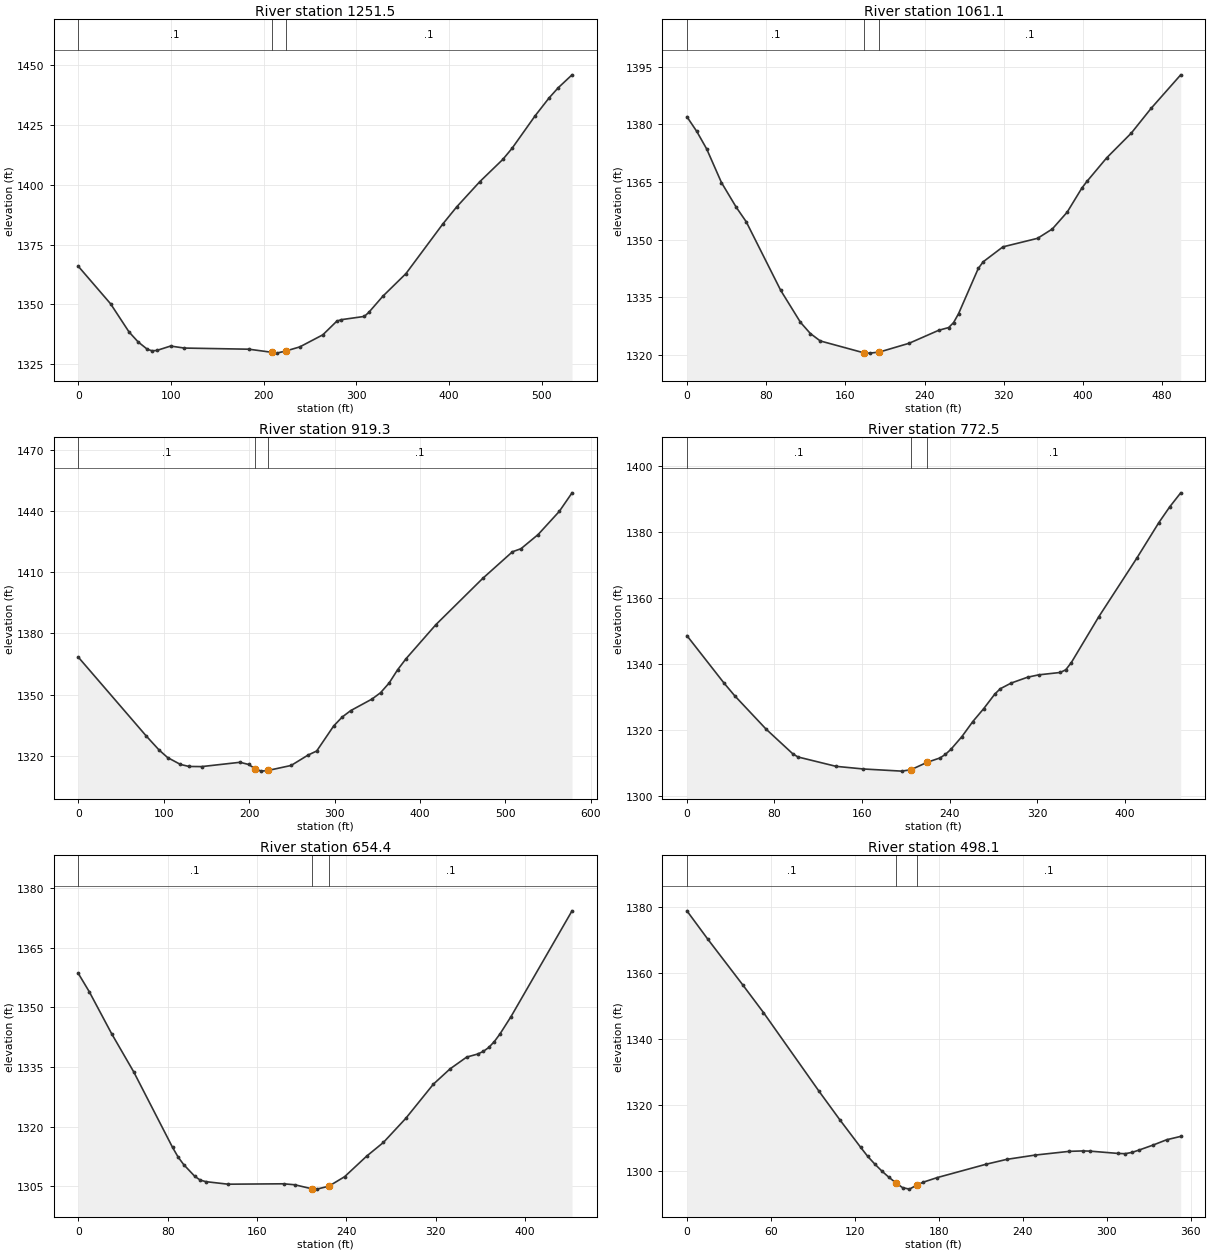
Type RM Length L Ch R = 1 ,1251.5  ,197.1,190.4,188
XS GIS Cut Line= 2
     1779505.868      201863.228     1779976.887      201614.132
#Sta/Elev= 30
       0 1365.93    34.9 1350.21    54.8 1338.43    64.7 1334.22    74.7 1331.13
    79.7 1330.54    84.7 1330.67    99.6 1332.52   114.5 1331.68   184.2  1331.2
   208.8 1329.91   214.1 1329.56   223.8 1330.43     239 1332.16   263.9 1337.22
   278.9  1342.9   283.8 1343.56   308.7 1344.92   313.7  1346.7   328.7 1353.39
   353.6 1362.85   393.4 1383.62   408.3 1390.74   433.2 1401.28   458.1 1410.62
   468.1 1415.28     493 1428.89   507.9  1436.3   517.9 1440.62   532.8 1446.02
#Mann= 3 , 0 , 0
       0      .1       0   208.8    .045       0   223.8      .1       0
Bank Sta=208.8,223.8
XS Rating Curve= 0 ,0
Exp/Cntr=0.3,0.1

Type RM Length L Ch R = 1 ,1061.1  ,133.7,141.8,150
XS GIS Cut Line= 2
     1779510.397       202039.86     1779931.596      201772.648
#Sta/Elev= 30
       0    1382      10 1378.16      20  1373.6    34.9 1364.87    49.9 1358.42
    59.9 1354.68    94.8  1336.8   114.7 1328.51   124.7 1325.59   134.7 1323.66
   179.3 1320.53   184.6 1320.49   194.3 1320.76   224.5 1323.06   254.4 1326.44
   264.4 1327.14   269.4 1328.45   274.4 1330.76   294.3 1342.52   299.3 1344.26
   319.2 1348.14   354.2 1350.36   369.1 1352.79   384.1 1357.17     399 1363.46
     404 1365.15     424  1371.3   448.9 1377.75   468.9 1384.18   498.8  1392.9
#Mann= 3 , 0 , 0
       0      .1       0   179.3    .045       0   194.3      .1       0
Bank Sta=179.3,194.3
XS Rating Curve= 0 ,0
Exp/Cntr=0.3,0.1

Type RM Length L Ch R = 1 ,919.3   ,142.8,146.7,150.7
XS GIS Cut Line= 2
     1779533.606      202106.035     1780094.802      201967.468
#Sta/Elev= 30
       0 1368.39    79.7 1329.68    94.7 1322.83   104.6 1319.16   119.6  1315.8
   129.6  1314.8   144.5 1314.73   189.4 1316.84   199.3 1315.78   207.4 1313.63
   214.3 1312.51   222.4 1312.86   249.2 1315.29   269.1  1320.4   279.1 1322.36
     299 1334.64     309 1339.02   318.9 1342.15   343.8 1347.81   353.8  1350.9
   363.8 1355.62   373.7 1362.08   383.7 1367.59   418.6 1384.26   473.4 1406.91
   508.3 1419.99   518.2 1421.46   538.2 1428.38   563.1 1439.77     578 1448.85
#Mann= 3 , 0 , 0
       0      .1       0   207.4    .045       0   222.4      .1       0
Bank Sta=207.4,222.4
XS Rating Curve= 0 ,0
Exp/Cntr=0.3,0.1

Type RM Length L Ch R = 1 ,772.5   ,112.2,118.2,124.2
XS GIS Cut Line= 3
     1779562.967      202169.956     1779662.823      202206.306
     1780005.817      202170.918
#Sta/Elev= 30
       0  1348.7    33.8 1334.38    43.5 1330.56    72.4 1320.37    96.6 1312.96
   101.4 1311.97   136.2 1309.13   161.2 1308.33   196.2 1307.68   204.6  1308.1
   219.6 1310.37   231.2 1311.67   236.2 1312.76   241.2 1314.29   251.2 1318.13
   261.2  1322.7   271.2 1326.63   281.2 1330.98   286.2 1332.61   296.2 1334.34
   311.2 1336.11   321.2 1336.82   341.1 1337.55   346.1 1338.37   351.1 1340.51
   376.1 1354.34   411.1 1372.22   431.1 1382.91   441.1 1387.71   451.1 1391.93
#Mann= 3 , 0 , 0
       0      .1       0   204.6    .045       0   219.6      .1       0
Bank Sta=204.6,219.6
XS Rating Curve= 0 ,0
Exp/Cntr=0.3,0.1

Type RM Length L Ch R = 1 ,654.4   ,156.8,156.3,155.7
XS GIS Cut Line= 2
     1779555.297      202268.916     1779990.845      202343.776
#Sta/Elev= 30
       0 1358.59     9.9 1353.95    29.8 1343.45    49.7 1333.78    84.4 1314.82
    89.4 1312.38    94.4 1310.48   104.3 1307.54   109.2 1306.59   114.2  1306.2
   134.1 1305.56   183.7 1305.66   193.7 1305.42   209.2  1304.4   213.5 1304.32
   224.2 1305.05   238.4 1307.45   258.2 1312.64   273.1 1316.06     293 1322.08
   317.8 1330.71   332.7 1334.55   347.6 1337.52   357.5 1338.29   362.5 1338.96
   367.4 1339.94   372.4 1341.44   377.4 1343.34   387.3 1347.71   441.9  1374.3
#Mann= 3 , 0 , 0
       0      .1       0   209.2    .045       0   224.2      .1       0
Bank Sta=209.2,224.2
XS Rating Curve= 0 ,0
Exp/Cntr=0.3,0.1

Type RM Length L Ch R = 1 ,498.1   ,168.2,168.2,168.3
XS GIS Cut Line= 2
      1779531.35      202404.446      1779880.45      202455.823
#Sta/Elev= 30
       0 1378.72    14.9 1370.15    39.8 1356.34    54.7 1347.91    94.4 1324.06
   109.3 1315.39   124.2 1307.04   129.2 1304.32   134.2 1302.02   139.2 1299.92
   144.1 1298.07   149.7 1296.18   154.1 1294.84     159 1294.39   164.7  1295.7
     169 1296.51   178.9 1297.89   213.7 1301.92   228.6 1303.41   248.5 1304.69
   273.3 1305.84   283.3 1305.97   288.2  1305.9   308.1 1305.21   313.1 1305.13
   318.1 1305.52     323 1306.21     333 1307.72   342.9 1309.36   352.9 1310.37
#Mann= 3 , 0 , 0
       0      .1       0   149.7    .045       0   164.7      .1       0
Bank Sta=149.7,164.7
XS Rating Curve= 0 ,0
Exp/Cntr=0.3,0.1

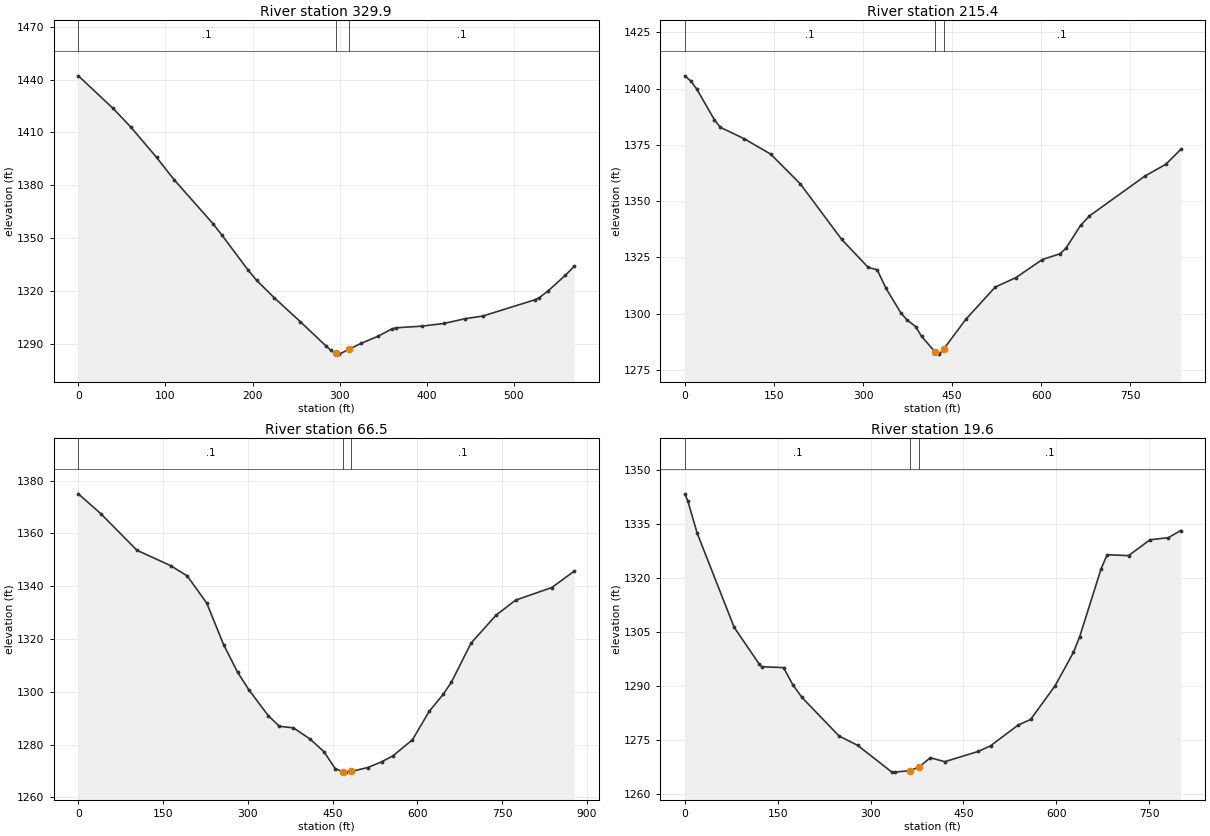
Type RM Length L Ch R = 1 ,329.9   ,116.6,114.5,108.2
XS GIS Cut Line= 2
     1779415.862      202549.722     1779982.619      202603.587
#Sta/Elev= 30
       0 1442.19      40 1423.62    59.9 1413.26    89.9 1395.79   109.9 1383.17
   154.8 1358.04   164.8 1351.68   194.8 1331.82   204.8 1325.88   224.7 1316.15
   254.7  1302.5   284.7 1288.46   289.6  1286.3   294.6  1284.5   295.6  1284.4
   299.6 1283.97   310.6 1286.68   324.6 1290.08   344.6 1294.24   359.6 1298.21
   364.6 1298.93   394.5 1299.88   419.5  1301.4   444.5 1304.13   464.4 1305.63
   524.4 1314.89   529.4 1316.13   539.4 1319.91   559.3 1328.84   569.3  1333.9
#Mann= 3 , 0 , 0
       0      .1       0   295.6    .045       0   310.6      .1       0
Bank Sta=295.6,310.6
XS Rating Curve= 0 ,0
Exp/Cntr=0.3,0.1

Type RM Length L Ch R = 1 ,215.4   ,144.8,148.9,157.2
XS GIS Cut Line= 3
     1779329.565      202672.352     1779757.851       202681.83
     1780158.725      202616.472
#Sta/Elev= 30
       0 1405.67      10  1403.4    19.9 1399.89    49.8 1386.18    59.8 1382.81
    99.6 1377.78   144.5 1370.92   194.3 1357.74     264 1333.05   308.8 1320.57
   323.8 1319.58   338.7  1311.3   363.6 1300.44   373.6 1297.38   388.5 1294.34
   398.5    1290   420.9  1283.2   428.4 1282.09   435.9  1284.4     473 1297.54
   522.5 1311.87   557.2 1316.05   601.8 1324.08   631.5 1326.65   641.4 1329.04
   666.2 1339.26     681 1343.44   775.1 1361.26   809.8 1366.41   834.6 1372.96
#Mann= 3 , 0 , 0
       0      .1       0   420.9    .045       0   435.9      .1       0
Bank Sta=420.9,435.9
XS Rating Curve= 0 ,0
Exp/Cntr=0.3,0.1

Type RM Length L Ch R = 1 ,66.5    ,43.4,46.9,51.6
XS GIS Cut Line= 5
     1779328.632      202714.871     1779555.806      202703.975
     1779740.739      202818.761     1779806.695      202832.828
     1780135.721      202674.176
#Sta/Elev= 30
       0 1375.01    39.6 1367.53   103.8 1353.63   163.2 1347.82   192.8 1343.92
   227.4 1333.59   257.1 1317.93   281.8  1307.5   301.6 1300.87   336.3 1290.97
     356 1286.95   380.8 1286.36   410.5 1282.09   435.2 1277.24   454.7 1270.94
     468 1269.73     474 1269.59     483 1269.84   512.5 1271.34   537.2 1273.52
     557 1275.77   591.5 1281.84   621.1  1292.6   645.8 1299.04   660.6 1303.71
   695.2 1318.44   739.6 1329.06   774.2 1334.75   838.3 1339.52   877.8  1345.7
#Mann= 3 , 0 , 0
       0      .1       0     468    .045       0     483      .1       0
Bank Sta=468,483
XS Rating Curve= 0 ,0
Exp/Cntr=0.3,0.1

Type RM Length L Ch R = 1 ,19.6    ,19.5,19.6,27.7
XS GIS Cut Line= 6
     1779398.821      202744.717     1779742.708      202863.125
     1779772.939      202875.721     1779796.873      202846.749
     1779892.607      202819.037     1780131.942      202700.629
#Sta/Elev= 30
       0  1343.3       5 1341.25    19.9 1332.41    79.7 1306.23   119.6 1296.17
   124.6 1295.28   159.4 1295.04   174.4 1290.29   189.3 1286.74   249.1 1276.04
     279 1273.46   333.8  1266.1   338.8 1266.01   363.4 1266.42   378.4 1267.44
   396.4 1270.01   419.9 1268.91   473.9 1271.76   493.8 1273.33   538.6 1279.11
   558.4 1280.63     598    1290   627.6 1299.27   637.5 1303.52   672.2 1322.43
     682 1326.38   716.7 1326.15   751.3 1330.54   780.9 1331.12   800.7 1333.11
#Mann= 3 , 0 , 0
       0      .1       0   363.4    .045       0   378.4      .1       0
Bank Sta=363.4,378.4
XS Rating Curve= 0 ,0
Exp/Cntr=0.3,0.1

Chan Stop Cuts=-1
Use User Specified Reach Order=0